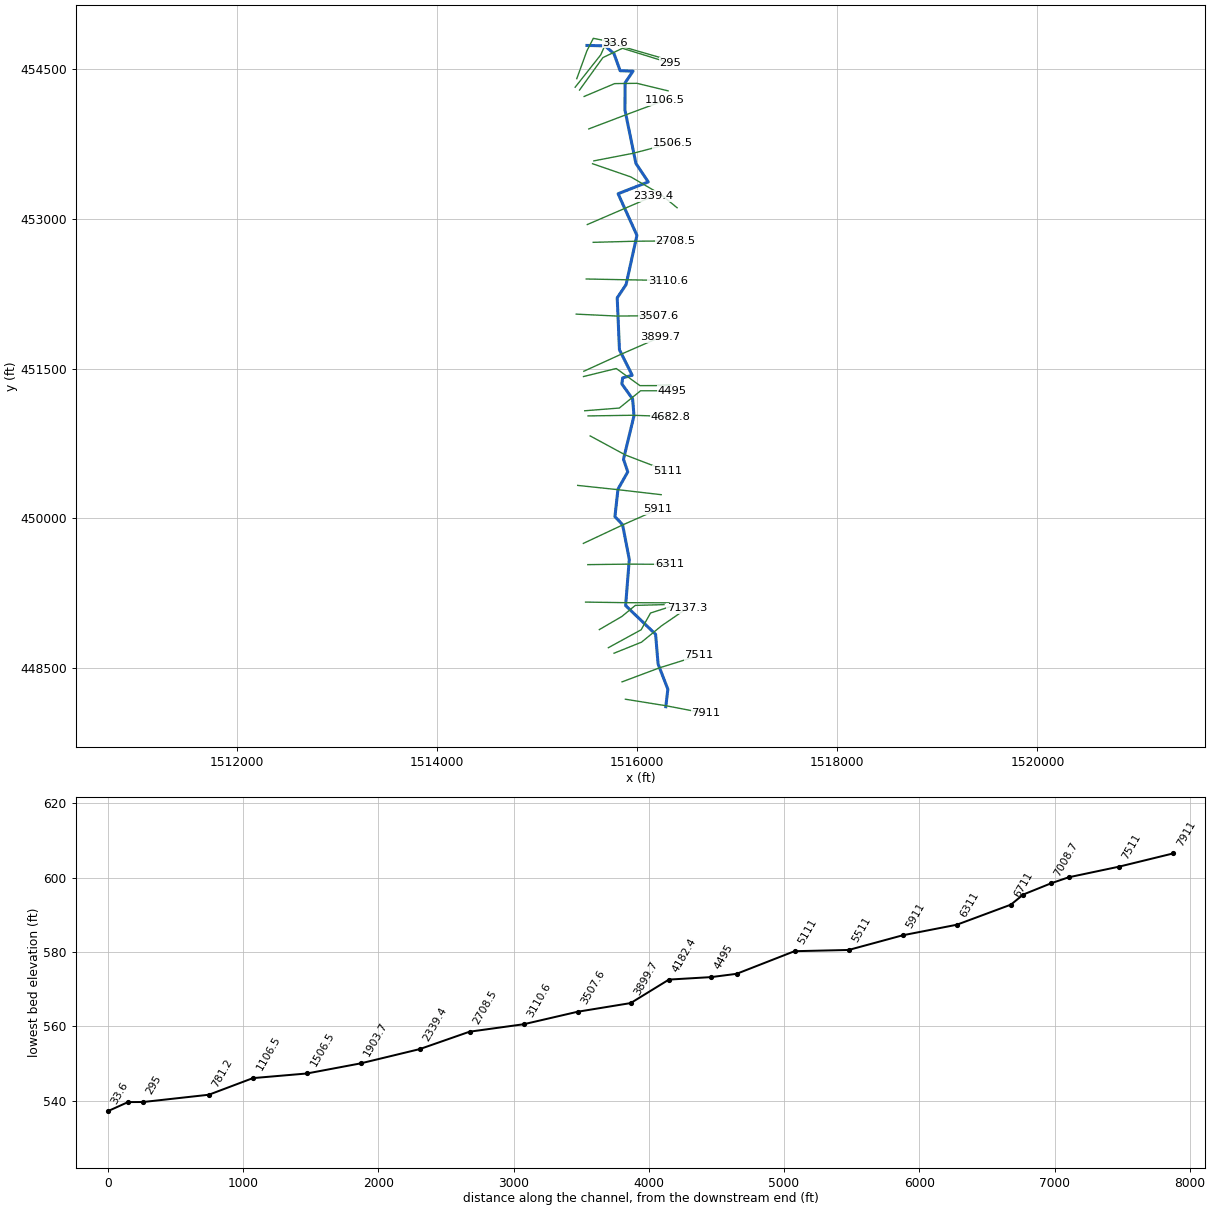
--- DAVISBR.prj (project) ---

Proj Title=DAVISBR
Current Plan=p01
Default Exp/Contr=0,0
English Units
Geom File=g01
Flow File=f01
Plan File=p01
BEGIN DESCRIPTION:
END DESCRIPTION:
DSS File=dss
DSS Export Rating Curves= 0
DSS Export Rating Curve Sorted= 0
DSS Export Volume Flow Curves= 0
DXF OffsetX= 0
DXF OffsetY= 0
DXF ScaleX= 0
DXF ScaleY= 0

--- DAVISBR.p01 (plan) ---

Plan Title=Floodplain
Program Version=4.00
Short Identifier=Floodplain
Geom File=g01
Flow File=f01
Subcritical Flow
K Sum by GR= 0
Std Step Tol= 0.01
Critical Tol= 0.01
Num of Std Step Trials= 20
Max Error Tol= 0.3
Flow Tol Ratio= 0.001
Split Flow NTrial= 30
Split Flow Tol= 0.02
Split Flow Ratio= 0.02
Log Output Level= 0
Friction Slope Method= 1
Unsteady Friction Slope Method= 2
Unsteady Bridges Friction Slope Method= 1
Parabolic Critical Depth
Global Vel Dist= 0 , 0 , 0
Global Log Level= 0
CheckData=True
Encroach Param=-1 ,0,0, 0
Run HTab= 0
Run UNet= 0
Run PostProcess= 0
Run WQNet= 0
UNET Theta= 0
UNET Theta Warmup= 0
UNET ZTol= 0
UNET ZSATol= 0
UNET MxIter= 0
UNET MaxInSteps= 0
UNET DtIC= 0
UNET DtMin= 0
UNET MaxCRTS= 0
UNET WFStab= 0
UNET SFStab= 0
UNET WFX= 1
UNET SFX= 1
UNET DSS MLevel= 1
UNET DZMax Abort= 0
UNET Convert EG Bridges= 0
UNET Use Existing IB Tables= 0
UNET Froude Reduction=False
UNET Froude Limit= 0
UNET Froude Power= 0
UNET Time Slicing=0,0, 5
DSS File=dss
Write IC File= 0
Echo Input=False
Echo Output=False
Write Detailed= 0
Detailed Automatic Start=False, 0
WQ ULTIMATE=-1
WQ Max Comp Step=1HOUR
WQ Output Interval=15MIN
WQ Output Selected Increments= 0
WQ Output face flow=0
WQ Output face velocity=0
WQ Output face area=0
WQ Output face dispersion=0
WQ Output cell volume=0
WQ Output cell surface area=0
WQ Output cell continuity=0
WQ Output face conc=0
WQ Output face dconc_dx=0
WQ Output face courant=0
WQ Output face peclet=0
WQ Output face adv mass=0
WQ Output face disp mass=0
WQ Output cell mass=0
WQ Output cell source sink temp=0
WQ Output cell source sink nsm=0
WQ Output MaxMinRange=-1
WQ Daily Max Min Mean=-1
WQ Daily Range=0
WQ Daily Time=0
WQ Create Restart=0
WQ Fixed Restart=0
WQ System Summary=False
Sorting and Armoring Iterations= 10
XS Update Threshold= 0.02
Hydraulics Update Threshold= 0.02
Energy Slope Method= 1
Volume Change Method= 0
XS Weighting Method= 0
Number of US Weighted Cross Sections= 1
Number of DS Weighted Cross Sections= 1
Upstream XS Weight=0.25
Main XS Weight=0.5
Downstream XS Weight=0.25
Number of DS XS's Weighted with US Boundary= 1
Upstream Boundary Weight= 1
Weight of XSs Associated with US Boundary= 0
Number of US XS's Weighted with DS Boundary= 1
Downstream Boundary Weight= 0.5
Weight of XSs Associated with DS Boundary= 0.5
Sediment Output Level= 4
Mass or Volume Output= 0
Output Increment Type= 1
Profile and TS Output Increment= 10
XS Output Flag= 0
XS Output Increment= 10
Disregard all LS=0
Disregard all Conn=0
Disregard all Breaches=0
Disregard all Pumps=0

--- DAVISBR.f01 (steady flow) ---

Flow Title=NFF Regression Equation
Program Version=4.00
Number of Profiles=1
Profile Names=P100yr
River Rch & RM=DAVISBR,Main      ,7911
     389
River Rch & RM=DAVISBR,Main      ,6311
     402
River Rch & RM=DAVISBR,Main      ,4495
     442
River Rch & RM=DAVISBR,Main      ,4182.4
     498
River Rch & RM=DAVISBR,Main      ,3899.7
     508
River Rch & RM=DAVISBR,Main      ,295
     559
Boundary for River Rch & Prof#=DAVISBR,Main      ,1
Up Type=0
Dn Type=3
Dn Slope=0.00688

--- DAVISBR.g01 (geometry) ---

Geom Title=USGS 10m DEM
Program Version=4.00

River Reach=DAVISBR         ,Main
Reach XY= 30
     1516285.047      448111.521     1516305.766      448286.537
     1516208.052      448539.678       1516183.2      448837.371
     1515883.498      449125.023      1515920.17       449587.92
     1515853.157      449935.235     1515776.613      450016.579
     1515807.248      450291.533     1515904.929      450464.852
     1515862.145       450591.29     1515967.219      451026.772
     1515953.651      451194.656     1515845.228      451346.754
     1515854.533      451406.856      1515949.13      451432.966
     1515821.843      451687.833     1515799.449      452208.195
     1515888.246      452341.568     1515996.512      452834.597
     1515808.467      453251.591     1516109.818      453369.858
     1515986.459      453554.995     1515876.665      454090.933
     1515878.616      454363.596     1515957.839      454480.206
     1515828.755      454484.111     1515766.923       454655.56
     1515677.068      454733.382     1515497.142      454737.449

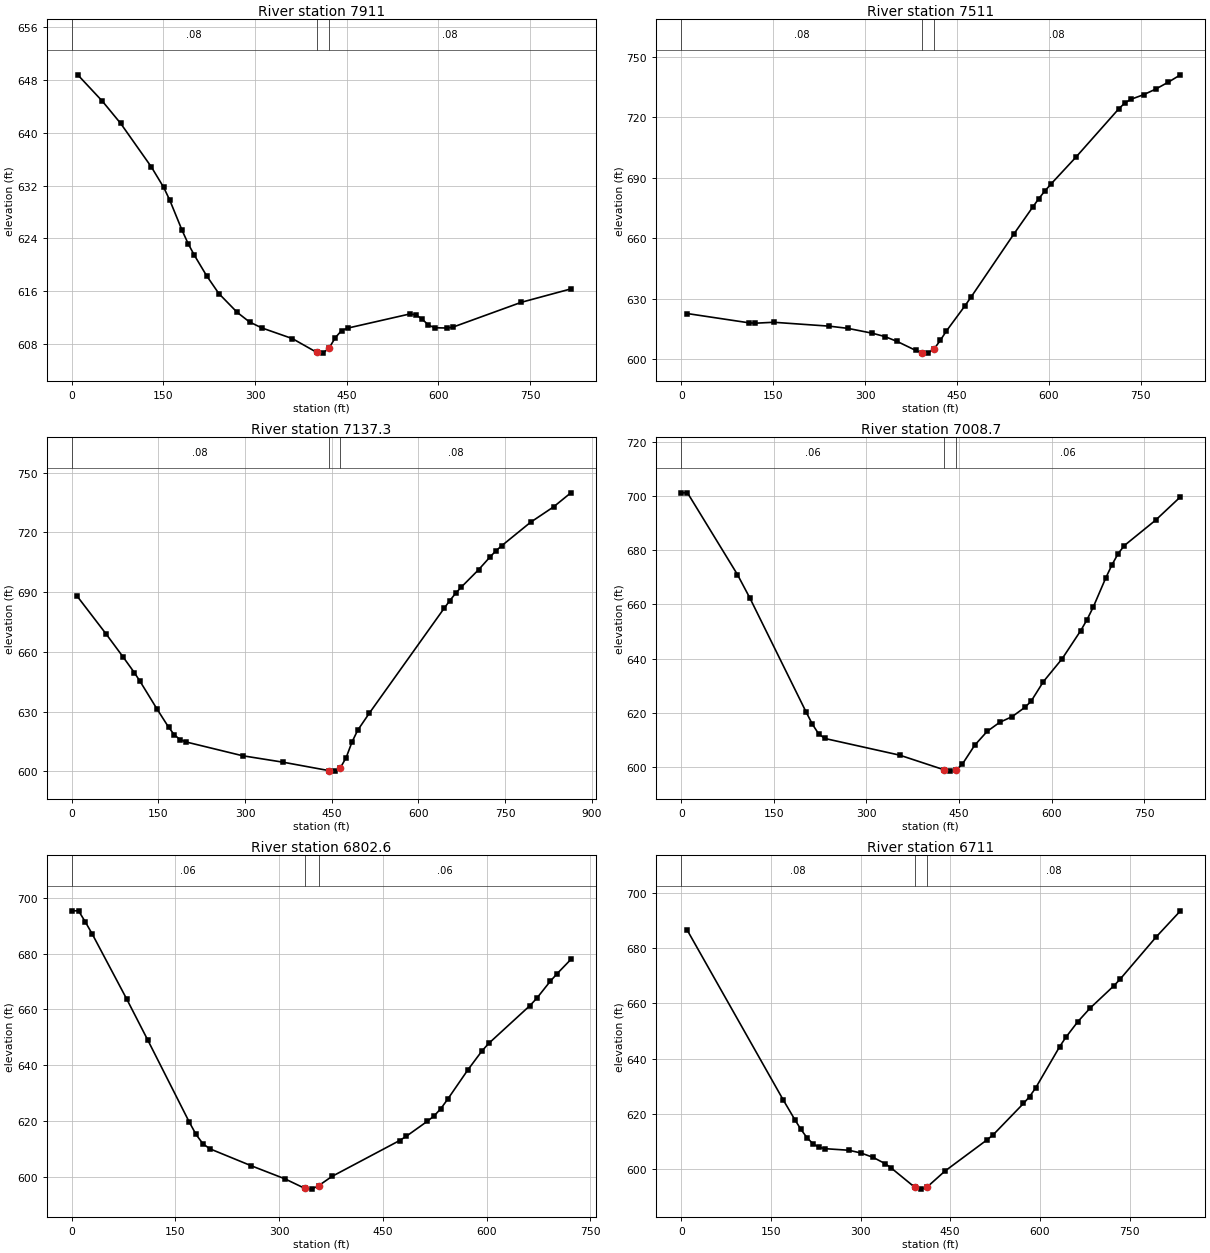
Type RM Length L Ch R = 1 ,7911    ,386.9,400,412.4
XS GIS Cut Line= 3
     1515881.381      448186.712      1516287.48       448121.22
     1516685.559      448044.838
#Sta/Elev= 30
      10  648.79    50.2   644.8    80.3  641.41   130.4  634.82   150.5  631.73
   160.5  629.79   180.6  625.22   190.6  623.18   200.7  621.43   220.7  618.33
   240.8  615.61   270.9  612.75     291   611.3     311   610.4   361.2  608.77
   401.3  606.67   411.3  606.57   421.3  607.37   431.6  608.94   441.7     610
   451.9  610.37   553.2  612.51   563.3  612.38   573.5  611.72   583.6  610.84
   593.7  610.42     614  610.38   624.2  610.53   735.6  614.28   816.7  616.31
#Mann= 3 , 0 , 0
       0     .08       0   401.3    .045       0   421.3     .08       0
Bank Sta=401.3,421.3
XS Rating Curve= 0 ,0
Exp/Cntr=0.3,0.1

Type RM Length L Ch R = 1 ,7511    ,365.6,373.7,383.2
XS GIS Cut Line= 3
     1515847.862      448360.492     1516224.946      448502.044
     1516618.307      448625.218
#Sta/Elev= 30
    10.1  622.61   110.8  618.02   120.8  617.84     151   618.3   241.7  616.37
   271.9  615.29   312.2  612.86   332.3  611.23   352.4  608.82   382.6  604.39
   392.8  603.14   402.8  603.01   412.8  605.08   422.9  609.31   432.9  613.97
   463.1  626.41   473.2  630.81   543.5  662.24   573.7  675.32   583.7  679.55
   593.8  683.41   603.8  686.86   644.1  700.03   714.4  724.11   724.5  727.04
   734.5  728.84   754.7  731.05   774.8  733.88   794.9  737.24     815  740.92
#Mann= 3 , 0 , 0
       0     .08       0   392.8    .045       0   412.8     .08       0
Bank Sta=392.8,412.8
XS Rating Curve= 0 ,0
Exp/Cntr=0.3,0.1

Type RM Length L Ch R = 1 ,7137.3  ,118.9,128.6,138.2
XS GIS Cut Line= 4
     1515767.633       448647.71      1516042.11      448758.095
     1516242.429      448921.992     1516497.173      449096.985
#Sta/Elev= 30
     9.9  687.85    59.2  669.18    88.8  657.56   108.5   649.6   118.3  645.26
   147.9  631.25   167.6  622.27   177.5  618.43   187.4     616   197.2  614.84
   295.8  607.86   365.5  604.64   445.1   600.4   455.1  600.14   465.1  601.91
     475  606.95     485  614.72   494.9  620.66   514.8  629.14   644.4  681.87
   654.4   685.8   664.3  689.41   674.3  692.58   704.2  701.31   724.2  707.78
   734.1  710.78   744.1  713.32   793.9  725.07   833.8  732.83   863.7  739.88
#Mann= 3 , 0 , 0
       0     .08       0   445.1    .045       0   465.1     .08       0
Bank Sta=445.1,465.1
XS Rating Curve= 0 ,0
Exp/Cntr=0.3,0.1

Type RM Length L Ch R = 1 ,7008.7  ,215.4,206.1,196.8
XS GIS Cut Line= 4
     1515710.774      448702.904      1516038.86       448882.57
     1516132.599      449050.519      1516363.04      449124.729
#Sta/Elev= 30
       0  701.12    10.1  701.12      91  671.01   111.2  662.33   202.2  620.35
   212.3  615.87   222.4  612.33   232.5  610.58   353.8  604.43   424.8   599.1
   434.8  598.54   444.8  598.91     455  601.02   475.3  608.09   495.5   613.2
   515.8  616.53     536  618.63   556.3  622.01   566.4  624.22   586.6  631.55
   616.8  639.93   647.1  650.36   657.2  654.37   667.3  659.02   687.4  669.68
   697.5  674.54   707.6  678.73   717.7   681.7   768.1  691.01   808.5  699.64
#Mann= 3 , 0 , 0
       0     .06       0   424.8    .045       0   444.8     .06       0
Bank Sta=424.8,444.8
XS Rating Curve= 0 ,0
Exp/Cntr=0.3,0.1

Type RM Length L Ch R = 1 ,6802.6  ,109.4,91.6,74.1
XS GIS Cut Line= 4
     1515620.941      448884.523     1515845.524      449015.367
     1515980.273      449126.682     1516267.348      449134.493
#Sta/Elev= 30
       0  695.38      10  695.38      20  691.32      30  686.97      80  663.56
     110  649.05   169.9  619.68   179.9  615.13   189.9  611.77   199.9  609.98
   259.9  603.88   308.5  599.19   337.3  595.77   347.3  595.51   357.3  596.77
   376.4  600.06   474.3  612.95   484.2  614.52   513.9  619.78   523.8   621.7
   533.7  624.33   543.6  627.71   573.3  638.42   593.1  645.01     603  647.77
   662.5  661.31   672.4  663.94   692.2  670.12   702.1  672.85   721.9  677.93
#Mann= 3 , 0 , 0
       0     .06       0   337.3    .045       0   357.3     .06       0
Bank Sta=337.3,357.3
XS Rating Curve= 0 ,0
Exp/Cntr=0.3,0.1

Type RM Length L Ch R = 1 ,6711    ,399,400,400.3
XS GIS Cut Line= 3
     1515483.128      449159.867     1515883.918      449154.064
     1516318.308      449152.663
#Sta/Elev= 30
      10  686.47   170.4  625.15   190.4  617.79   200.4  614.36   210.4  611.38
   220.5  609.18   230.5  607.92   240.5  607.42   280.6  606.85   300.6  605.86
   320.7  604.31   340.7  602.05   350.7  600.54   390.8  593.45   400.8  592.79
   410.8  593.44   441.2  599.32     512  610.68   522.1  612.49   572.6  623.78
   582.7  626.24   592.8  629.34   633.2  644.35   643.3  647.66   663.5  653.36
   683.7  658.18   724.1  666.39   734.2  668.72   794.8  684.06   835.2  693.45
#Mann= 3 , 0 , 0
       0     .08       0   390.8    .045       0   410.8     .08       0
Bank Sta=390.8,410.8
XS Rating Curve= 0 ,0
Exp/Cntr=0.3,0.1

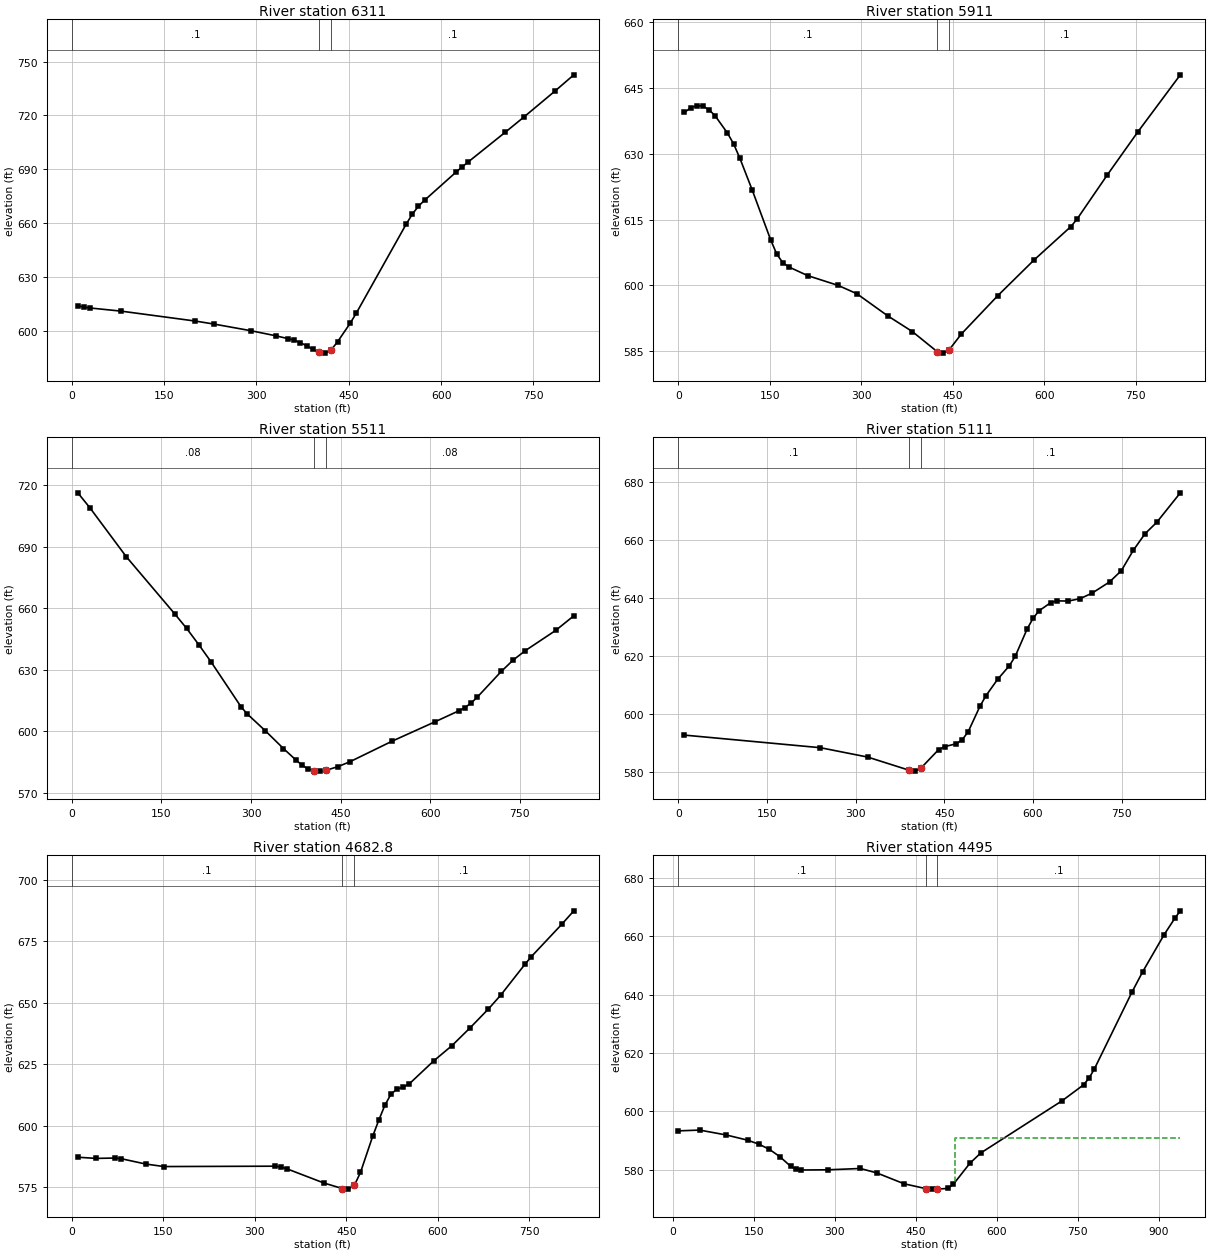
Type RM Length L Ch R = 1 ,6311    ,389.2,400,410.7
XS GIS Cut Line= 3
     1515505.651        449535.3     1515917.411       449540.19
     1516321.343      449538.125
#Sta/Elev= 30
      10  613.84    20.1     613    30.1  612.56    80.3  610.81   200.9  605.27
     231   603.6   291.3  599.87   331.4  597.06   351.5  595.45   361.6  594.55
   371.6  593.23   381.7  591.43   391.7  589.47   401.8   587.8   411.8  587.38
   421.8  589.34     432   593.8   452.2  603.99   462.3  609.72   543.1  659.23
   553.2  664.89   563.3  669.39   573.4  672.76   623.9  688.26     634  691.22
   644.1  694.07   704.6  710.72   734.9  719.22   785.4  733.72   815.7  742.68
#Mann= 3 , 0 , 0
       0      .1       0   401.8    .045       0   421.8      .1       0
Bank Sta=401.8,421.8
XS Rating Curve= 0 ,0
Exp/Cntr=0.3,0.1

Type RM Length L Ch R = 1 ,5911    ,413.8,400,388
XS GIS Cut Line= 3
     1515461.084      449748.031     1515853.768      449932.838
     1516209.043      450090.519
#Sta/Elev= 30
    10.1  639.44    20.2  640.49    30.3  640.98    40.4   640.9    50.5  640.07
    60.6  638.65    80.7  634.74    90.8  632.26   100.9  629.03   121.1   621.8
   151.4   610.4   161.5  607.11   171.6  605.13   181.7  604.17     212  602.23
   262.4  599.97   292.7  598.09   343.2  593.05   383.5  589.47     424  584.91
     434  584.54     444  585.31   463.9   588.9   523.7  597.66   583.5  605.85
   643.3   613.4   653.3  615.08   703.1   625.2   752.9  634.97   822.7  648.03
#Mann= 3 , 0 , 0
       0      .1       0     424    .045       0     444      .1       0
Bank Sta=424,444
XS Rating Curve= 0 ,0
Exp/Cntr=0.3,0.1

Type RM Length L Ch R = 1 ,5511    ,410.6,400,391.4
XS GIS Cut Line= 3
     1515404.264      450329.045     1515806.826       450286.31
     1516239.394      450236.206
#Sta/Elev= 30
    10.1  716.41    30.4  709.09    91.1  685.28   172.1  657.42   192.3  650.23
   212.5  642.34   232.8  634.05   283.4  611.95   293.5  608.54   323.9  600.29
   354.2  591.63   374.5   586.2   384.6  583.69   394.7   581.7     405  580.71
     415  580.59     425  580.95   445.3  582.76   465.6  585.18   536.5  595.26
   607.4  604.59   647.9  610.04     658   611.6   668.1  613.76   678.3  616.57
   718.8  629.24     739  634.86   759.3  639.43   809.9  649.26   840.3   656.4
#Mann= 3 , 0 , 0
       0     .08       0     405    .045       0     425     .08       0
Bank Sta=405,425
XS Rating Curve= 0 ,0
Exp/Cntr=0.3,0.1

Type RM Length L Ch R = 1 ,5111    ,415.5,428.2,437.1
XS GIS Cut Line= 3
     1515529.172      450825.022     1515881.276      450633.878
     1516300.097      450472.946
#Sta/Elev= 30
      10  592.68   240.4  588.33   320.5   585.1   390.6  580.57   400.6  580.26
   410.6  581.31   440.5  587.68   450.5  588.68   470.4   589.7   480.4  591.08
   490.4   593.8   510.3  602.57   520.3  606.17   540.2  611.87   560.2  616.58
   570.1  619.84   590.1  629.19   600.1  632.86     610  635.45     630  638.29
   639.9  638.92   659.9  638.85   679.8  639.69   699.8  641.55   729.7  645.45
   749.6  649.34   769.6  656.28   789.5  662.02   809.4  665.97   849.3  676.14
#Mann= 3 , 0 , 0
       0      .1       0   390.6    .045       0   410.6      .1       0
Bank Sta=390.6,410.6
XS Rating Curve= 0 ,0
Exp/Cntr=0.3,0.1

Type RM Length L Ch R = 1 ,4682.8  ,169.5,187.8,206.6
XS GIS Cut Line= 3
     1515507.926      451025.341     1515951.054      451031.865
     1516330.448      451019.271
#Sta/Elev= 30
    10.1  587.15    40.3  586.68    70.5  586.83    80.6  586.58   120.9   584.4
   151.1  583.36   332.4  583.51   342.5   583.2   352.5  582.45     413  576.68
   443.2  574.42   453.2  574.17   463.2  575.75   473.1  580.94   493.1  595.65
   503.1  602.24   513.1   608.3   523.1  612.84   533.1  614.92   543.1  615.69
   553.1  617.02     593  626.34     623  632.58     653  639.89   682.9  647.54
   702.9  653.12   742.9  665.78   752.9  668.76   802.8  681.94   822.8  687.47
#Mann= 3 , 0 , 0
       0      .1       0   443.2    .045       0   463.2      .1       0
Bank Sta=443.2,463.2
XS Rating Curve= 0 ,0
Exp/Cntr=0.3,0.1

Type RM Length L Ch R = 1 ,4495    ,331.1,312.6,276.6
XS GIS Cut Line= 4
      1515474.54      451076.938     1515820.545      451104.254
     1516033.005      451277.257     1516351.694      451277.257
#Sta/Elev= 30
     9.9  593.27    49.6  593.54    99.2  591.85   138.8  590.06   158.7  588.75
   178.5  586.97   198.3  584.39   218.2  581.11   228.1  580.09     238  579.85
   287.6  579.92   347.1  580.37   377.5  578.86   428.3  575.12     469  573.44
     479  573.29     489   573.3   509.4  573.53   519.6  574.98     550  582.15
   570.3   585.7   720.7  603.57   760.5  609.04   770.5   611.3   780.4  614.42
   850.1  640.81     870  647.81   909.9  660.59   929.8  666.23   939.8  668.74
#Mann= 3 , 0 , 0
     9.9      .1       0     469    .045       0     489      .1       0
#XS Ineff= 2 , 0
                          523.29          590.86
Permanent Ineff=
       F       F
Bank Sta=469,489
XS Rating Curve= 0 ,0
Exp/Cntr=0.3,0.1

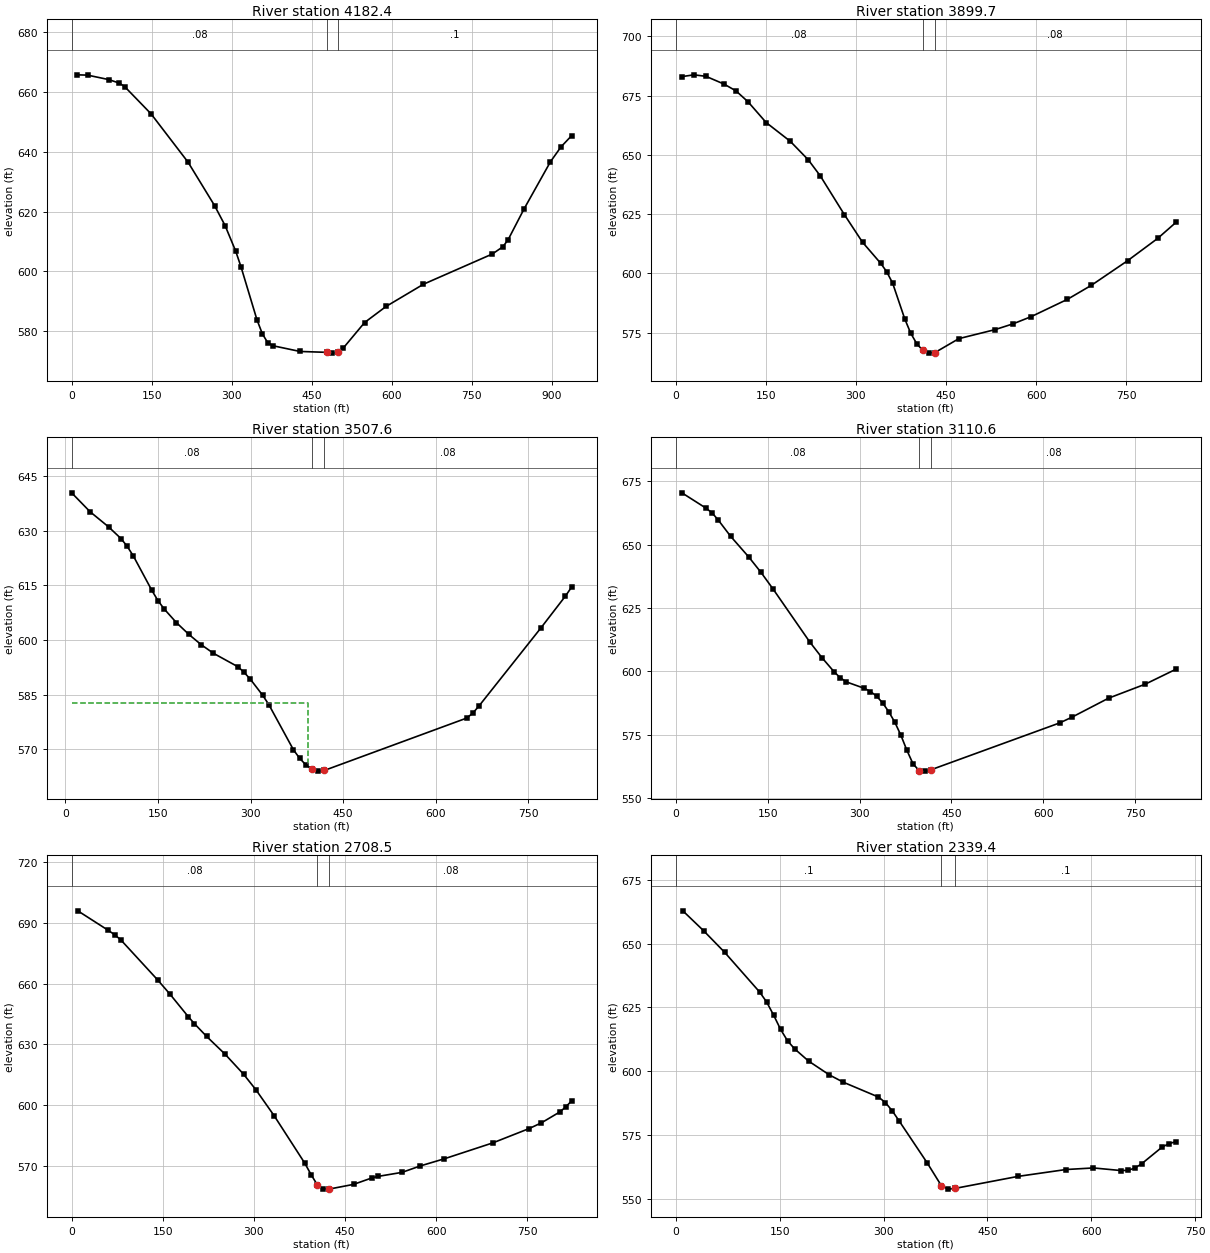
Type RM Length L Ch R = 1 ,4182.4  ,270.9,282.7,307.4
XS GIS Cut Line= 4
     1515462.399      451419.908     1515789.899      451500.331
     1516026.935      451328.854     1516334.419      451329.673
#Sta/Elev= 30
     9.9  665.79    29.8  665.69    69.4   664.2    89.3  663.02    99.2  661.87
   148.8  652.73   218.2  636.54   267.8  622.04   287.6  615.33   307.5  606.76
   317.4  601.54   347.3  583.81   357.4  579.11   367.5  576.13   377.6  575.08
     428  573.18   478.6  572.88   488.6  572.62   498.6   572.9   508.7  574.22
   549.1  582.86   589.4  588.25   659.5  595.69   788.5   605.8   808.3  608.22
   818.2   610.6     848  620.88   897.6  636.71   917.4  641.69   937.3  645.44
#Mann= 3 , 0 , 0
       0     .08       0   478.6    .045       0   498.6      .1       0
Bank Sta=478.6,498.6
XS Rating Curve= 0 ,0
Exp/Cntr=0.3,0.1

Type RM Length L Ch R = 1 ,3899.7  ,403.9,392.1,382.3
XS GIS Cut Line= 3
     1515465.737      451472.889     1515848.797      451648.101
      1516225.91      451812.841
#Sta/Elev= 30
      10  683.04    30.1   683.8    50.1  683.17    80.2   679.9   100.3     677
   120.4  672.37   150.4  663.66   190.6  655.73   220.6  647.91   240.7  641.09
   280.8  624.74   310.9  613.13     341  604.28     351  600.75   361.1  595.83
   381.1  580.86   391.1  574.76   401.2   570.3   411.2  567.47   421.2   566.3
   431.2  566.49   471.4  572.42   531.6  576.22   561.8  578.68   591.9  581.71
   652.1     589   692.2  594.95   752.5  605.33   802.6  614.75   832.8  621.46
#Mann= 3 , 0 , 0
       0     .08       0   411.2    .045       0   431.2     .08       0
Bank Sta=411.2,431.2
XS Rating Curve= 0 ,0
Exp/Cntr=0.3,0.1

Type RM Length L Ch R = 1 ,3507.6  ,396.2,396.9,396.2
XS GIS Cut Line= 3
     1515389.748      452045.293     1515798.666      452025.769
      1516209.47      452030.135
#Sta/Elev= 30
      10  640.36    39.9  635.16    69.9     631    89.9  627.81    99.8  625.71
   109.8  623.07   139.8  613.62   149.8  610.78   159.8   608.5   179.7  604.74
   199.7  601.53   219.7   598.7   239.6  596.33   279.6   592.6   289.6  591.05
   299.5   589.2   319.5   584.8   329.5  582.22   369.4  569.82   379.4   567.5
   389.4   565.7   399.4  564.45   409.4  563.97   419.4  564.16   649.9  578.52
   659.9  579.86   669.9  581.83   770.1  603.22   810.2  612.04   820.2  614.51
#Mann= 3 , 0 , 0
      10     .08       0   399.4    .045       0   419.4     .08       0
#XS Ineff= 2 , 0
          392.52  582.66
Permanent Ineff=
       F       F
Bank Sta=399.4,419.4
XS Rating Curve= 0 ,0
Exp/Cntr=0.3,0.1

Type RM Length L Ch R = 1 ,3110.6  ,401.4,402.2,402.6
XS GIS Cut Line= 3
     1515489.716      452397.222     1515886.957      452389.661
     1516306.167      452382.046
#Sta/Elev= 30
     9.9  670.46    49.7  664.34    59.6  662.44    69.5  659.64    89.4  653.32
   119.2   645.1   139.1  639.05   158.9  632.45   218.5  611.67   238.4  605.46
   258.3  599.87   268.2  597.53   278.1  595.87   307.9  593.29   317.9  592.04
   327.8  590.22   337.7  587.55   347.6  584.11   357.6  579.93   367.5   574.8
   377.4   568.8   387.4  563.47   397.3  560.84   407.3  560.62   417.3  561.21
   626.9  579.65   646.9  581.91   706.8  589.42   766.7  594.95   816.6  600.82
#Mann= 3 , 0 , 0
       0     .08       0   397.3    .045       0   417.3     .08       0
Bank Sta=397.3,417.3
XS Rating Curve= 0 ,0
Exp/Cntr=0.3,0.1

Type RM Length L Ch R = 1 ,2708.5  ,359.4,369.1,379.1
XS GIS Cut Line= 3
      1515559.42      452764.616     1515973.387      452775.443
     1516382.045      452779.649
#Sta/Elev= 30
    10.1  695.88    60.6  686.18    70.7  684.09    80.8  681.58   141.4  661.83
   161.6  654.84   191.9  643.66     202  640.21   222.2  633.89   252.5  625.15
   282.8  615.32     303  607.69   333.3  594.77   383.8  571.31   393.9   565.8
   404.1  560.77   414.1   558.6   424.1  558.65   463.9  560.94   493.9  564.11
   503.8  564.86   543.7  566.87   573.6  570.03   613.5  573.59   693.2  581.43
     753   588.5   772.9  591.28   802.9   596.6   812.8  599.06   822.8  602.17
#Mann= 3 , 0 , 0
       0     .08       0   404.1    .045       0   424.1     .08       0
Bank Sta=404.1,424.1
XS Rating Curve= 0 ,0
Exp/Cntr=0.3,0.1

Type RM Length L Ch R = 1 ,2339.4  ,454.7,435.7,427.5
XS GIS Cut Line= 3
     1515500.416      452942.816     1515944.986       453134.76
     1516163.516      453228.849
#Sta/Elev= 30
    10.1  662.81    40.4  654.94    70.6  646.54   121.1  631.01   131.1  627.15
   141.2  622.01   151.3  616.41   161.4  611.92   171.5  608.81   191.7  604.02
   221.9  598.58   242.1  595.72   292.6  589.95   302.6   587.8   312.7   584.5
   322.8  580.48   363.2  564.12   383.4   555.3   393.4  553.91   403.4   554.2
   494.1  558.89   563.5  561.58   603.2   562.2   642.9  561.18   652.8  561.26
   662.7   562.1   672.6  563.78   702.3  570.35   712.2  571.69   722.2  572.49
#Mann= 3 , 0 , 0
       0      .1       0   383.4    .045       0   403.4      .1       0
Bank Sta=383.4,403.4
XS Rating Curve= 0 ,0
Exp/Cntr=0.3,0.1

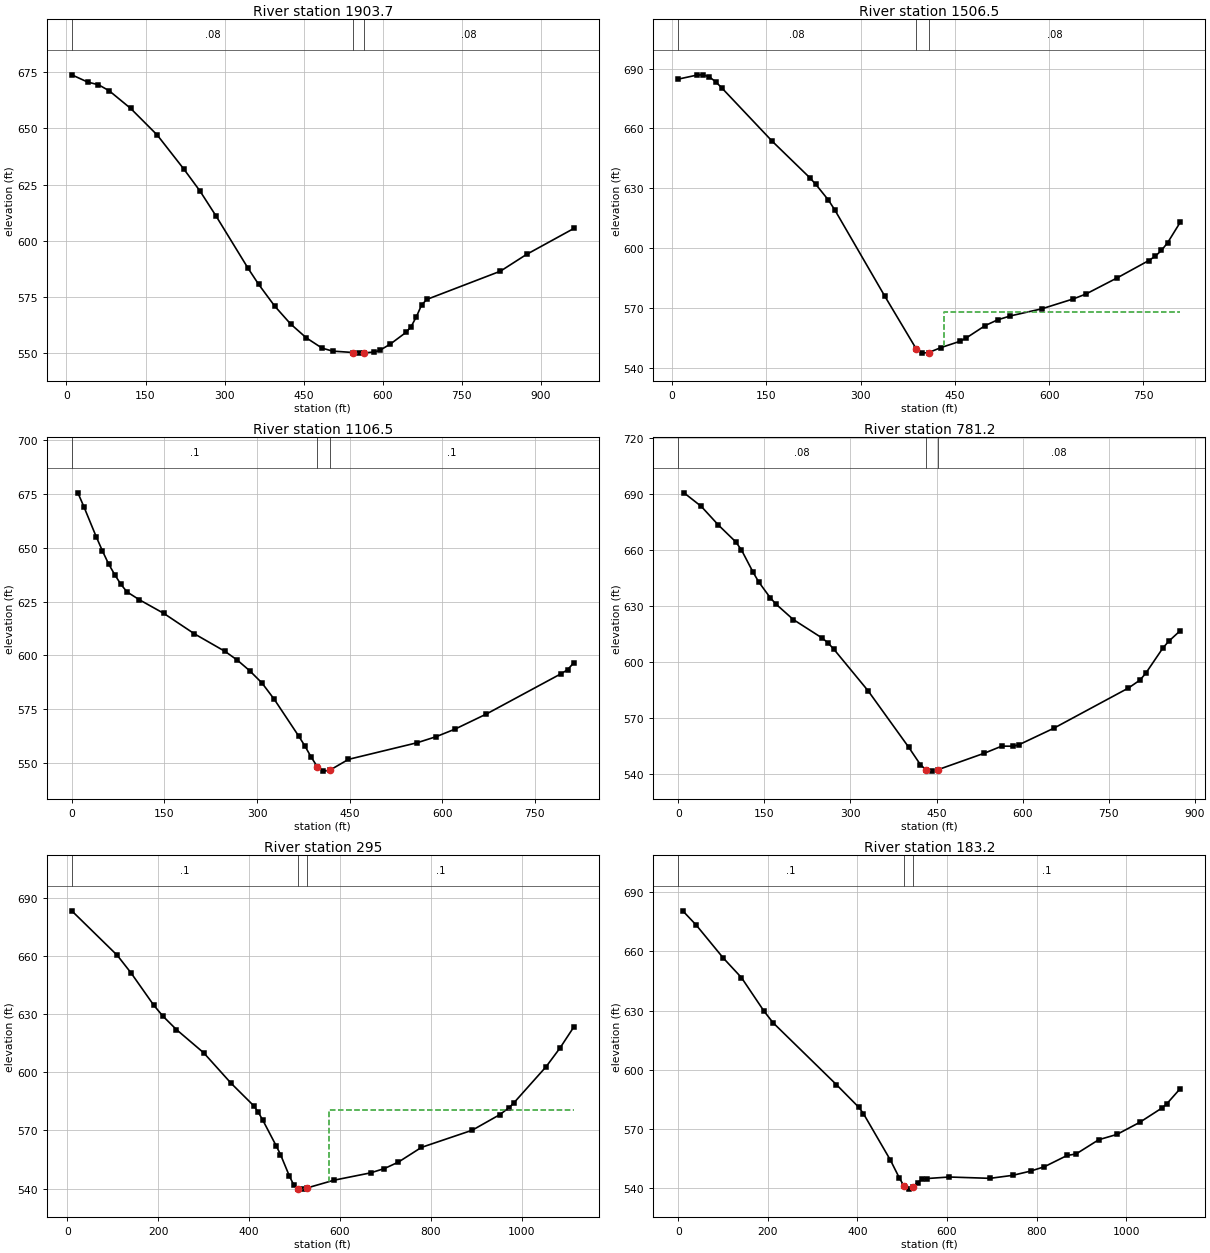
Type RM Length L Ch R = 1 ,1903.7  ,375.9,397.2,402.9
XS GIS Cut Line= 4
     1515552.817      453552.388     1515935.881      453420.062
     1516236.359      453244.025     1516397.913      453111.303
#Sta/Elev= 30
    10.1  673.73    40.5  670.49    60.8  669.32    81.1  666.64   121.6  658.85
   172.2  646.99   222.9   631.8   253.3  622.12   283.7  611.04   344.5   587.8
   364.7  580.61   395.1  570.97   425.2  563.05     455  556.88   484.9  552.31
   504.8  550.98   544.5  550.35  554.83  550.08   564.5   550.2   584.4  550.57
   594.3   551.3   614.2  554.06   644.1  559.28     654  561.89     664  566.32
   673.9  571.54   683.9  573.96   823.2  586.48     873  593.96   962.6  605.47
#Mann= 3 , 0 , 0
    10.1     .08       0   544.5    .045       0   564.5     .08       0
Bank Sta=544.5,564.5
XS Rating Curve= 0 ,0
Exp/Cntr=0.3,0.1

Type RM Length L Ch R = 1 ,1506.5  ,395.7,400,402.5
XS GIS Cut Line= 3
     1515565.594      453580.924     1515956.647      453656.472
     1516353.728      453760.344
#Sta/Elev= 30
      10  684.68    39.8   686.7    49.8  686.83    59.7  685.74    69.7  683.32
    79.7  680.14   159.3  653.61   219.1  635.32     229  631.87   248.9  624.06
   258.9  619.21   338.5  575.95   388.3  549.65   398.3  547.36   408.3  547.64
   428.3  550.18   458.3  553.29   468.4  555.01   498.4  561.18   518.4  564.08
   538.4  566.01   588.5  569.58   638.5  574.53   658.6  576.98   708.6  585.13
   758.7  593.78   768.7   595.9   778.7  598.82   788.7  602.79   808.7     613
#Mann= 3 , 0 , 0
      10     .08       0   388.3    .045       0   408.3     .08       0
#XS Ineff= 2 , 0
                          433.22             568
Permanent Ineff=
       F       F
Bank Sta=388.3,408.3
XS Rating Curve= 0 ,0
Exp/Cntr=0.3,0.1

Type RM Length L Ch R = 1 ,1106.5  ,334.4,325.3,316.2
XS GIS Cut Line= 3
     1515515.068      453901.071     1515895.793       454046.02
     1516275.816      454187.952
#Sta/Elev= 30
     9.9  675.59    19.9  668.94    39.7  655.08    49.7  648.55    59.6  642.52
    69.6  637.49    79.5  633.04    89.4   629.5   109.3  625.87     149   619.5
   198.7  609.97   248.4  601.78   268.3   597.7   288.1  592.82     308  587.11
   327.9  579.52   367.6  562.35   377.6  557.76   387.5  552.71   397.4  548.25
   407.4  546.11   417.4  546.47     448  551.58   559.5  559.34   589.9  562.13
   620.4  565.63   671.1  572.64   792.8   591.5   802.9  593.29     813  596.59
#Mann= 3 , 0 , 0
       0      .1       0   397.4    .045       0   417.4      .1       0
Bank Sta=397.4,417.4
XS Rating Curve= 0 ,0
Exp/Cntr=0.3,0.1

Type RM Length L Ch R = 1 ,781.2   ,465.7,486.2,498.1
XS GIS Cut Line= 4
     1515469.174      454226.316     1515773.638      454355.112
     1515996.583      454357.919     1516308.777      454282.428
#Sta/Elev= 30
      10  690.56    40.1  683.31    70.1  673.28   100.2  664.32   110.2  659.97
   130.2  648.18   140.2  642.89   160.3  634.41   170.3  631.01   200.4  622.76
   250.4  612.92   260.5  610.37   270.5   607.1   330.6  584.69   401.5  554.43
   421.8  545.15   432.1  542.16   442.1  541.64   452.1  542.37   533.3  551.23
   563.6  555.01   583.7  554.97   593.7  555.78   653.9  564.53   784.4  586.12
   804.5  590.37   814.5  594.01   844.6  607.63   854.7  611.18   874.7  616.82
#Mann= 3 , 0 , 0
       0     .08       0   432.1    .045       0   452.1     .08       0
Bank Sta=432.1,452.1
XS Rating Curve= 0 ,0
Exp/Cntr=0.3,0.1

Type RM Length L Ch R = 1 ,295     ,93.9,111.7,129.6
XS GIS Cut Line= 4
     1515422.936      454290.726     1515656.648      454615.906
     1515851.784      454708.814     1516327.413      454561.273
#Sta/Elev= 30
      10  683.51   110.1  660.51   140.2  651.48   190.2  634.79   210.2  629.16
   240.3  622.13   300.3  610.12   360.4  594.42   410.3  582.77   420.1  579.48
   429.9  575.49   459.4  562.22   469.2  557.57   488.9  546.37   498.7   541.7
   508.3  539.73   518.3  539.68   528.3  540.33   587.1  544.31   667.4  548.08
   697.9  550.32   728.4  553.62   779.2  561.24     891  570.12     952  578.22
   972.3  581.82   982.4   584.2  1053.6  602.96  1084.1   612.6  1114.6  623.51
#Mann= 3 , 0 , 0
      10      .1       0   508.3    .045       0   528.3      .1       0
#XS Ineff= 2 , 0
                          576.72          580.74
Permanent Ineff=
       F       F
Bank Sta=508.3,528.3
XS Rating Curve= 0 ,0
Exp/Cntr=0.3,0.1

Type RM Length L Ch R = 1 ,183.2   ,156,149.7,143.3
XS GIS Cut Line= 4
      1515378.89      454318.677     1515634.852      454643.244
     1515691.901      454772.176      1516236.01      454614.235
#Sta/Elev= 30
    10.1  680.43    40.3  673.18   100.8   656.5   141.1  646.66   191.6  629.65
   211.7  623.82   352.9  592.57   403.3  581.01   413.4  577.87   473.8   554.3
   493.9  545.19   504.1  541.17   514.1  539.66   524.1  540.78   534.2  542.99
   544.3  544.59   554.3     545   604.9  545.79     696  545.12   746.6  546.63
     787   548.8   817.4  550.98     868  556.67   888.2  557.45   938.8  564.65
   979.3  567.32  1029.9  573.39  1080.4  580.76  1090.6  582.79  1120.9  590.54
#Mann= 3 , 0 , 0
       0      .1       0   504.1    .045       0   524.1      .1       0
Bank Sta=504.1,524.1
XS Rating Curve= 0 ,0
Exp/Cntr=0.3,0.1

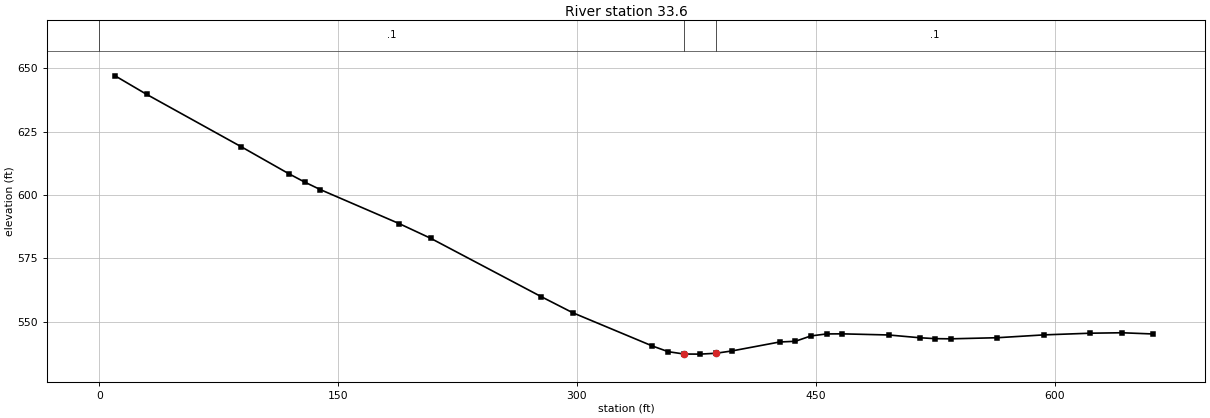
Type RM Length L Ch R = 1 ,33.6    ,9,33.6,58.1
XS GIS Cut Line= 4
     1515395.242      454404.775     1515496.791      454684.319
     1515560.687      454808.688     1515780.899       454765.33
#Sta/Elev= 30
     9.9  647.07    29.7  639.76    89.2  619.05     119  608.43   128.9  605.15
   138.8  602.16   188.4  588.71   208.2  582.91   277.6  559.88   297.4  553.53
   347.4  540.41   357.3  538.17   367.3  537.24   377.3   537.2   387.3  537.54
   397.3  538.45   427.3  541.99   437.2  542.27     447  544.39   456.8  545.17
   466.5  545.21   495.8  544.76   515.3  543.67   525.1  543.31   534.8  543.24
   564.1  543.68   593.4   544.8   622.6  545.46   642.2  545.64   661.7  545.16
#Mann= 3 , 0 , 0
       0      .1       0   367.3    .045       0   387.3      .1       0
Bank Sta=367.3,387.3
XS Rating Curve= 0 ,0
Exp/Cntr=0.3,0.1

Chan Stop Cuts=-1
Use User Specified Reach Order=0